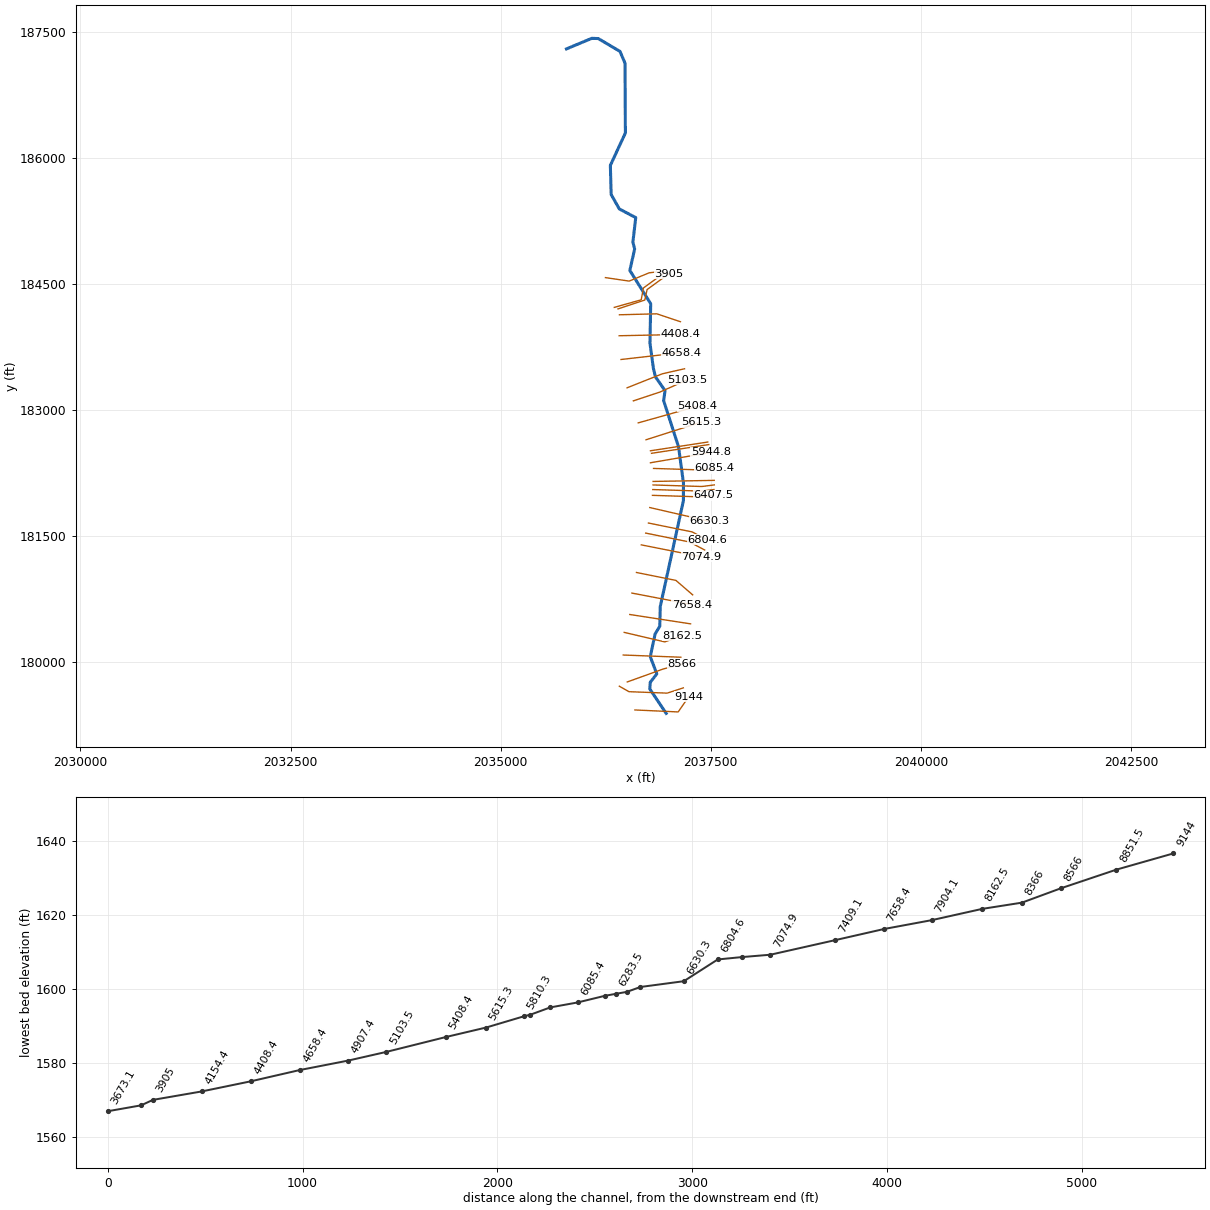
--- FITZRN.prj (project) ---

Proj Title=FITZRN
Current Plan=p01
Default Exp/Contr=0,0
English Units
Geom File=g01
Flow File=f01
Plan File=p01
BEGIN DESCRIPTION:
END DESCRIPTION:
DSS Export Rating Curves= 0
DSS Export Rating Curve Sorted= 0
DSS Export Volume Flow Curves= 0
DXF OffsetX= 0
DXF OffsetY= 0
DXF ScaleX= 0
DXF ScaleY= 0

--- FITZRN.p01 (plan) ---

Plan Title=Floodplain
Program Version=4.00
Geom File=g01
Flow File=f01
K Sum by GR=0
Std Step Tol=0.01
Critical Tol=0.01
Num of Std Step Trials=20
Max Error Tol=0.3
Flow Tol Ratio=0.001
Split Flow NTrial=30
Split Flow Tol=0.02
Split Flow Ratio=0.02
Log Output Level=0
Friction Slope Method=1
Unsteady Friction Slope Method=2
Unsteady Bridges Friction Slope Method=1
Global Log Level=0
CheckData=False
Run HTab=0
Run UNet=0
Run PostProcess=0
UNET Theta=0
UNET Theta Warmup=0
UNET ZTol=0
UNET ZSATol=0
UNET MxIter=0
UNET MaxInSteps=0
UNET DtIC=0
UNET DtMin=0
UNET MaxCRTS=0
UNET WFStab=0
UNET SFStab=0
UNET WFX=0
UNET SFX=0
UNET DSS MLevel=0
UNET DZMax Abort=0
UNET Convert EG Bridges=0
UNET Use Existing IB Tables=0
UNET Froude Limit=0
UNET Froude Power=0
Write IC File=0
Echo Input=False
Echo Output=False
Write Detailed=0

--- FITZRN.f01 (steady flow) ---

Flow Title=NFF Regression Equation
Program Version=4.10
Number of Profiles= 1
Profile Names=P100yr
River Rch & RM=FITZRN,Main            ,9144
459.1654
River Rch & RM=FITZRN,Main            ,8851.5
 461.457
River Rch & RM=FITZRN,Main            ,8566
 676.561
River Rch & RM=FITZRN,Main            ,6804.6
709.7286
River Rch & RM=FITZRN,Main            ,6407.5
 820.279
River Rch & RM=FITZRN,Main            ,4154.4
860.6917
River Rch & RM=FITZRN,Main            ,3364
954.5536
River Rch & RM=FITZRN,Main            ,436.4
1042.486
River Rch & RM=FITZRN,Main            ,47
1044.354
Boundary for River Rch & Prof#=FITZRN,Main            , 1
Up Type= 0
Dn Type= 3
Dn Slope=0.013648
DSS Import GetInterval= 0
DSS Import GetPeak= 0
DSS Import FillOption= 0

--- FITZRN.g01 (geometry) ---

Geom Title=USGS 10m DEM
Program Version=4.10

River Reach=FITZRN          ,Main
Reach XY= 30
      2036969.54      179391.961     2036775.053      179681.769
     2036779.666      179760.948     2036858.075       179861.65
     2036780.434      180066.899     2036838.088      180337.489
     2036893.703      180428.837     2036898.912      180662.344
     2037174.317      181921.603     2037175.185      182132.541
     2037116.811      182563.363     2036939.074      183114.311
     2036956.435      183232.367      2036842.72      183394.693
     2036817.546      183497.124     2036776.747      183796.603
     2036785.428      184267.089     2036537.164      184662.054
     2036594.456      184918.131     2036573.622       184998.86
     2036607.477      185291.395     2036412.164      185393.825
     2036314.942        185565.7     2036305.393      185912.054
     2036484.213      186298.339     2036479.872        187128.2
     2036419.922      187268.801     2036161.296      187421.603
     2036084.039      187424.207     2035783.138      187298.578

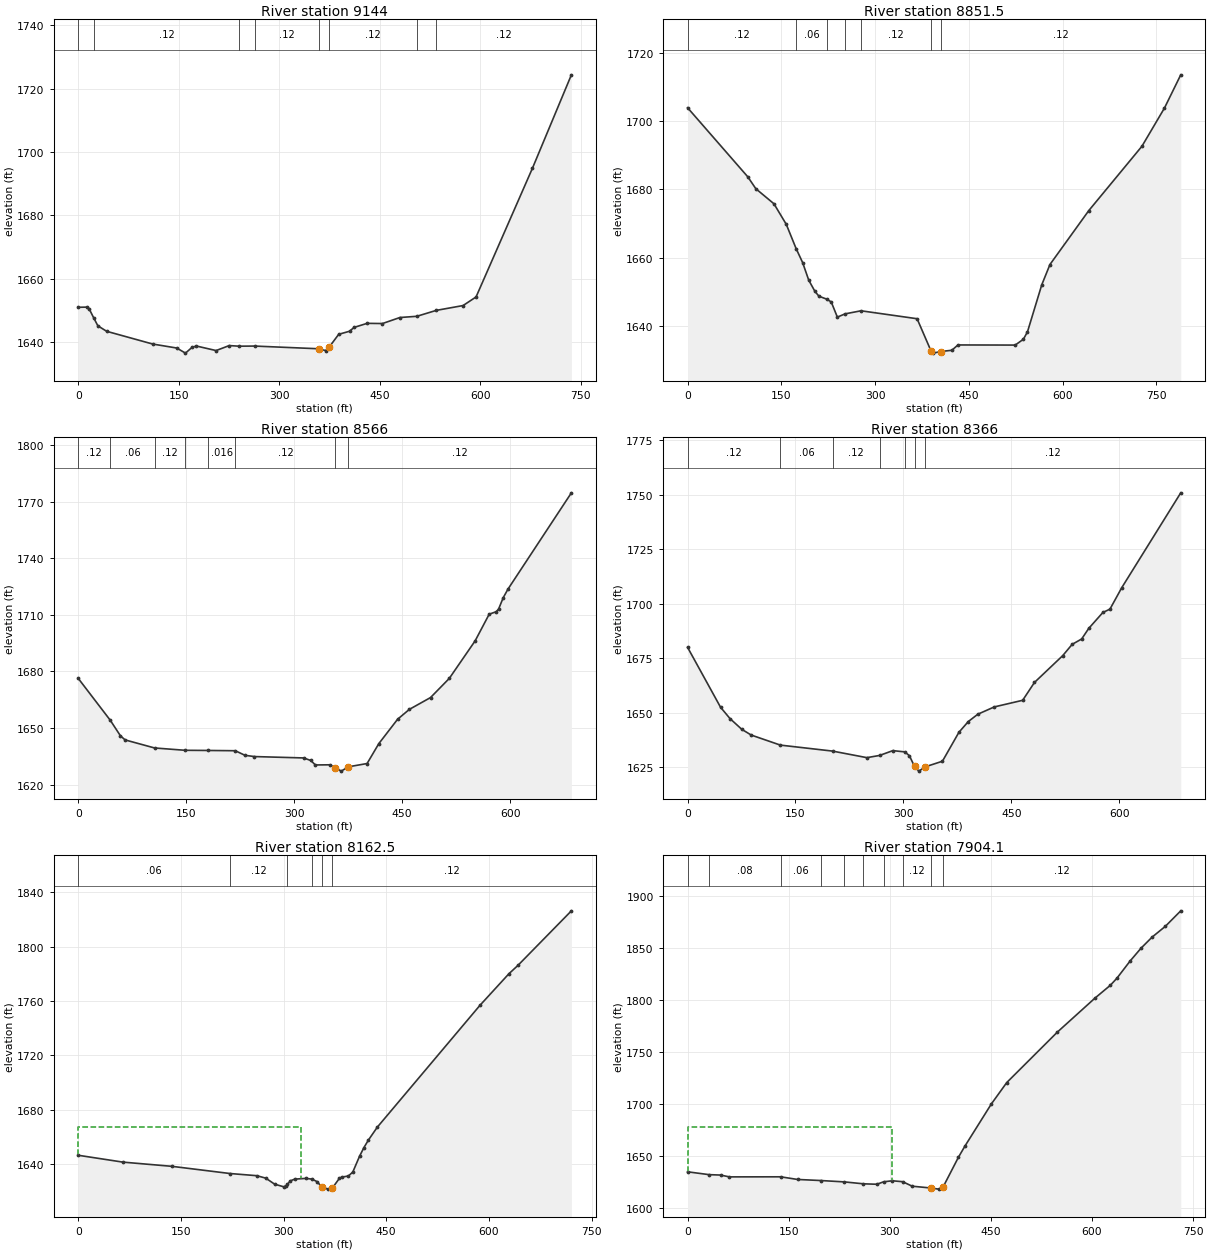
Type RM Length L Ch R = 1 ,9144    ,290.7,292.6,291.1
XS GIS Cut Line= 3
     2036597.059      179432.651     2037112.684      179409.214
     2037237.684      179590.203
#Sta/Elev= 30
       0 1651.02    13.1 1651.08    16.3 1650.55   23.441647.565    29.4 1645.17
    42.5 1643.45   111.1 1639.44     147 1638.18   160.1 1636.57   169.9 1638.39
   176.4 1638.81   205.8 1637.38   225.4 1638.95  240.08 1638.76  263.431638.797
   359.4 1637.94   369.2 1637.37  374.75 1638.52   388.8  1642.5   405.1 1643.48
   411.6 1644.67   431.2 1645.96   454.1  1645.9   480.2  1647.8  505.371648.181
  534.481650.049   574.4 1651.57   593.8 1654.28   677.9 1694.84   736.1 1724.32
#Mann= 8 ,-1 , 0
       0    .016       0   23.44     .12       0  240.08     .06       0
  263.43     .12       0   359.4    .045       0  374.75     .12       0
  505.37     .06       0  534.48     .12       0
Bank Sta=359.4,374.75
XS Rating Curve= 0 ,0
Exp/Cntr=0.3,0.1

Type RM Length L Ch R = 1 ,8851.5  ,274.9,285.5,295
XS GIS Cut Line= 4
     2036412.163      179715.203     2036526.747      179650.099
     2036981.062      179632.846     2037173.882      179695.672
#Sta/Elev= 30
       0 1703.88    96.4 1683.69   109.3 1680.21   138.3 1675.81     158  1669.8
  173.681662.741   184.1 1658.66   193.9 1653.51   203.8 1650.23   210.3 1648.81
  222.481647.973   229.9 1647.15   239.7 1642.71  252.041643.659  277.591644.558
   367.3 1642.24   389.9 1632.69   393.4 1632.19   404.9 1632.66   422.9 1633.02
   432.7 1634.58   524.3 1634.54   537.4 1636.25   543.9  1638.4   566.8 1652.15
   579.9 1658.08     642 1673.82   727.1 1692.63   763.1 1703.78   789.2 1713.49
#Mann= 7 ,-1 , 0
       0     .12       0  173.68     .06       0  222.48     .08       0
  252.04    .016       0  277.59     .12       0   389.9    .045       0
   404.9     .12       0
Bank Sta=389.9,404.9
XS Rating Curve= 0 ,0
Exp/Cntr=0.3,0.1

Type RM Length L Ch R = 1 ,8566    ,209,200,190.6
XS GIS Cut Line= 3
     2036507.215      179765.984     2036936.903      179920.932
     2037158.257      179976.922
#Sta/Elev= 30
       0 1676.33   44.54 1654.11    58.7 1645.85    65.2 1643.68  106.121639.416
   148.51638.184   179.91638.095  218.261637.949   231.6 1635.53   244.7 1634.86
   313.2 1634.13     323 1632.79   329.5 1630.41   349.1 1630.49   357.4  1628.9
   365.4 1627.14   375.2 1629.42   401.3 1631.17   417.6 1641.72   443.7 1654.65
     460 1659.87   489.4 1666.13   515.5  1676.3   551.4 1696.21   570.9 1710.33
   580.7 1711.65     584 1713.09   590.5 1719.14     597 1723.62   685.1 1774.66
#Mann= 8 ,-1 , 0
       0     .12       0   44.54     .06       0  106.12     .12       0
   148.5     .08       0   179.9    .016       0  218.26     .12       0
   357.4    .045       0   375.2     .12       0
Bank Sta=357.4,375.2
XS Rating Curve= 0 ,0
Exp/Cntr=0.3,0.1

Type RM Length L Ch R = 1 ,8366    ,207.7,203.5,199.1
XS GIS Cut Line= 2
     2036459.038      180086.297     2037143.934      180060.255
#Sta/Elev= 30
       0 1680.03    45.9 1652.53      59 1647.35    75.4 1642.42    88.5  1639.8
  129.041635.187   201.51632.449   249.2 1629.44  266.811630.448   285.3 1632.66
  301.881632.083   308.3 1630.34   315.4 1625.42   321.4 1623.26   330.4 1625.24
   354.2  1627.8   377.1 1641.06   390.2 1646.01   403.4 1649.36   426.3 1652.71
   465.7 1655.74   482.1 1663.93   521.4 1676.23   534.5  1681.4   547.7 1683.86
   557.5  1688.7   577.2 1696.02     587 1697.54   603.4 1707.38   685.4 1750.88
#Mann= 7 ,-1 , 0
       0     .12       0  129.04     .06       0   201.5     .12       0
  266.81    .016       0  301.88     .12       0   315.4    .045       0
   330.4     .12       0
Bank Sta=315.4,330.4
XS Rating Curve= 0 ,0
Exp/Cntr=0.3,0.1

Type RM Length L Ch R = 1 ,8162.5  ,256.5,258.4,260.1
XS GIS Cut Line= 3
     2036469.854      180355.726     2036952.528      180242.547
     2037164.767      180316.766
#Sta/Elev= 30
       0 1646.51    65.2 1641.47     137 1638.36  221.731633.075   260.9 1631.47
     274 1629.68     287 1625.23   300.1 1623.33   303.3 1623.73  305.751625.066
   309.8 1627.65   316.4 1628.95   332.7 1629.48   341.51628.962     349  1627.1
   356.4 1622.86   365.3 1621.58   371.4 1622.42   381.6  1629.5   384.9 1630.43
   394.7 1631.22   401.2 1634.14     411 1645.71   417.5  1652.2     424 1657.69
   437.1 1667.25     587 1756.89   629.4 1780.19   642.4 1786.25   720.6 1826.47
#Mann= 6 ,-1 , 0
       0     .06       0  221.73     .12       0  305.75    .016       0
   341.5     .12       0   356.4    .045       0   371.4     .12       0
#XS Ineff= 2 , 0
          325.16 1667.26
Permanent Ineff=
       F       F
Bank Sta=356.4,371.4
XS Rating Curve= 0 ,0
Exp/Cntr=0.3,0.1

Type RM Length L Ch R = 1 ,7904.1  ,246.4,245.7,244.5
XS GIS Cut Line= 2
     2036536.615      180568.565      2037259.82      180457.391
#Sta/Elev= 30
       0 1635.18   31.981632.441      49 1632.05    62.1  1630.3  138.111630.368
   163.3 1627.82  197.241626.812  232.631625.486  260.991623.639   280.9 1623.22
  290.871625.573   303.8 1626.56  319.131625.675   333.2 1621.36   361.7 1619.57
   372.4 1618.54   378.9 1620.31   401.8 1649.07   411.6 1659.97   450.8 1700.44
   473.6 1720.92   548.8 1769.44   604.3 1801.91   627.2 1814.28     637  1821.1
   656.6 1837.64   672.9 1850.02   689.2 1860.56   708.8  1870.9   731.7 1885.81
#Mann= 10 ,-1 , 0
       0     .06       0   31.98     .08       0  138.11     .06       0
  197.24    .016       0  232.63     .06       0  260.99     .12       0
  290.87    .016       0  319.13     .12       0   361.7    .045       0
   378.9     .12       0
#XS Ineff= 2 , 0
             303 1678.21
Permanent Ineff=
       F       F
Bank Sta=361.7,378.9
XS Rating Curve= 0 ,0
Exp/Cntr=0.3,0.1

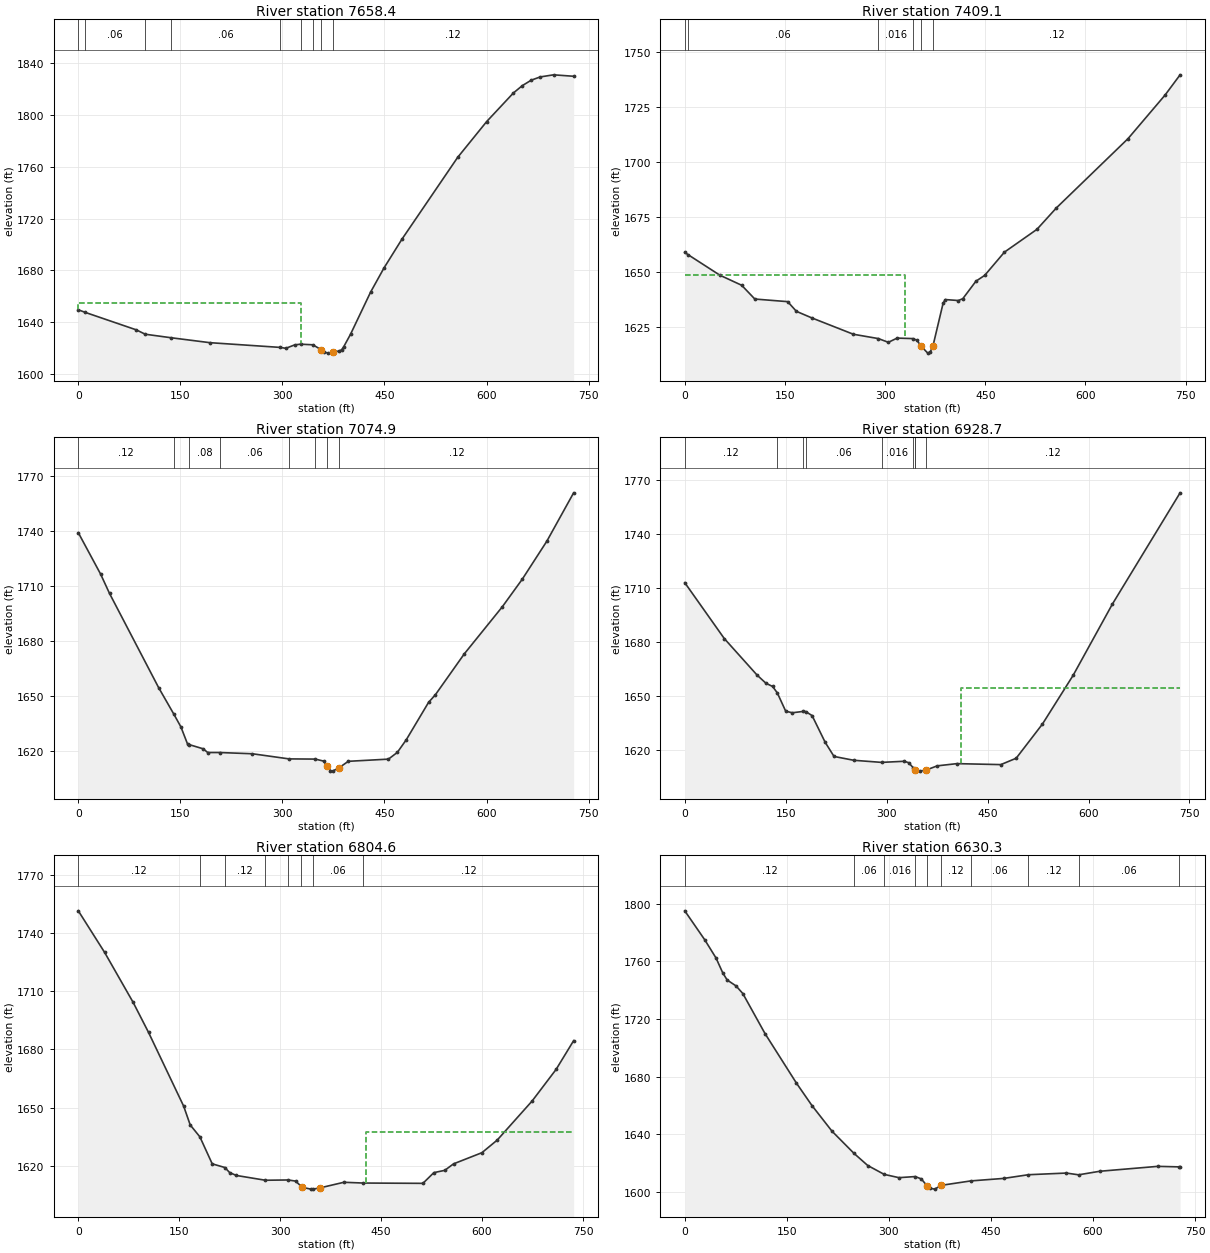
Type RM Length L Ch R = 1 ,7658.4  ,249.3,249.3,249
XS GIS Cut Line= 2
     2036562.301      180823.231      2037277.31      180686.313
#Sta/Elev= 30
       0 1649.63   10.241647.603    85.3  1634.1    98.4 1630.74  136.471628.018
   193.5 1624.21  296.631620.565     305 1619.87   318.1 1622.52  326.711623.047
  344.77 1622.57   357.4 1618.64   360.7 1617.04   367.3 1616.14   373.8 1616.88
   383.7  1617.8     387 1618.73   390.2 1621.18   400.1 1630.72   429.6 1663.28
   449.3 1681.94   475.5 1704.03   557.5 1767.32   600.1 1794.96   639.5 1817.12
   652.6 1822.78   665.7 1826.98   678.8 1829.49   698.5 1831.12     728 1830.01
#Mann= 9 ,-1 , 0
       0     .12       0   10.24     .06       0    98.4     .08       0
  136.47     .06       0  296.63     .12       0  326.71    .016       0
  344.77     .12       0   357.4    .045       0   373.8     .12       0
#XS Ineff= 2 , 0
          327.42 1654.76
Permanent Ineff=
       F       F
Bank Sta=357.4,373.8
XS Rating Curve= 0 ,0
Exp/Cntr=0.3,0.1

Type RM Length L Ch R = 1 ,7409.1  ,334.2,334.2,334.3
XS GIS Cut Line= 3
     2036615.989      181068.378      2037085.34      180974.318
     2037284.559      180802.443
#Sta/Elev= 30
       0 1659.02    4.941657.957    52.5 1648.63    85.2 1644.04   104.9 1637.77
   154.1 1636.58   167.2 1632.17   190.2 1629.19   252.5 1621.74  289.941619.769
   304.9 1618.07     318 1619.99  341.421619.767   347.5 1619.06   354.1 1616.27
   363.9 1613.15   367.2 1613.48   371.5 1616.17   386.9 1635.89   390.2 1637.53
   409.8 1637.09   416.4 1637.94   436.1  1645.9   449.2 1648.55   478.7 1659.11
   527.4 1669.49   556.6 1679.27   663.8 1710.77   719.1 1730.54   741.8 1739.82
#Mann= 6 ,-1 , 0
       0     .12       0    4.94     .06       0  289.94    .016       0
  341.42     .12       0   354.1    .045       0   371.5     .12       0
#XS Ineff= 2 , 0
          329.23  1648.5
Permanent Ineff=
       F       F
Bank Sta=354.1,371.5
XS Rating Curve= 0 ,0
Exp/Cntr=0.3,0.1

Type RM Length L Ch R = 1 ,7074.9  ,146.2,146.2,146
XS GIS Cut Line= 3
     2036673.739      181396.935     2037030.784      181326.123
      2037387.83       181255.31
#Sta/Elev= 30
       0 1739.13    32.8 1716.56    45.9 1706.02     118 1654.74  140.341640.284
   150.8 1633.29   160.7 1623.82  163.191623.616   183.6 1621.35   190.2 1619.33
  207.631619.329   255.8 1618.66  309.761615.855  348.291615.751   360.7 1614.64
  365.45  1611.9   370.6  1609.5   373.8 1609.19   383.7 1611.14   396.8 1614.54
   455.8 1615.73   468.9  1619.4     482 1626.27   514.8 1646.67   524.7 1650.76
   567.3  1673.1   623.1 1698.72   652.6 1713.84   688.6  1734.5     728 1760.87
#Mann= 8 ,-1 , 0
       0     .12       0  140.34     .06       0  163.19     .08       0
  207.63     .06       0  309.76    .016       0  348.29     .12       0
  365.45    .045       0   383.7     .12       0
Bank Sta=365.45,383.7
XS Rating Curve= 0 ,0
Exp/Cntr=0.3,0.1

Type RM Length L Ch R = 1 ,6928.7  ,124.1,124.1,124.1
XS GIS Cut Line= 3
     2036725.816      181537.244     2037246.799      181431.349
     2037427.788      181336.297
#Sta/Elev= 30
       0 1712.93    58.7 1681.99   107.6 1661.69   120.7 1657.21   130.5 1655.45
  137.481651.903     150 1641.75   159.8 1640.88  175.961641.623  179.651641.548
   189.2 1639.32   208.7 1624.49   221.8 1616.68   251.1 1614.56  292.421613.394
   326.2 1614.01   332.7 1613.23  339.611610.365  341.411609.686   342.3 1609.35
     349 1608.55   358.8 1609.15   375.1 1611.47   404.4  1612.7   469.7 1612.16
   492.5 1615.69   531.6 1634.66   577.1 1661.58   635.5 1701.08   736.1  1762.7
#Mann= 9 ,-1 , 0
       0     .12       0  137.48     .06       0  175.96     .08       0
  179.65     .06       0  292.42    .016       0  339.61     .06       0
  341.41     .12       0   342.3    .045       0   358.8     .12       0
#XS Ineff= 2 , 0
                          411.08         1654.64
Permanent Ineff=
       F       F
Bank Sta=342.3,358.8
XS Rating Curve= 0 ,0
Exp/Cntr=0.3,0.1

Type RM Length L Ch R = 1 ,6804.6  ,174.8,174.3,173.6
XS GIS Cut Line= 3
     2036758.368      181657.036     2037279.351      181551.141
      2037460.34      181456.089
#Sta/Elev= 30
       0 1751.44    39.1    1730    81.5 1704.22   104.4 1688.72   156.6 1650.68
   166.3 1641.02  180.671634.876     199 1620.95  217.761619.062     225 1616.43
   234.8 1614.96  278.051612.489  311.851612.635   322.9 1612.05   330.5 1609.59
   332.7 1608.85   345.5 1607.91     349 1607.92   358.8 1608.52   394.6 1611.44
   423.61611.051   512.1 1610.89   528.4 1616.42   544.6  1617.6   557.6 1620.94
   599.8  1626.7   622.5 1633.19   674.4 1653.35   710.1 1669.68   736.1 1684.48
#Mann= 8 ,-1 , 0
       0     .12       0  180.67     .06       0  217.76     .12       0
  278.05    .016       0  311.85     .06       0   330.5    .045       0
     349     .06       0   423.6     .12       0
#XS Ineff= 2 , 0
                          426.91         1637.14
Permanent Ineff=
       F       F
Bank Sta=332.7,358.8
XS Rating Curve= 0 ,0
Exp/Cntr=0.3,0.1

Type RM Length L Ch R = 1 ,6630.3  ,218.2,222.8,227.1
XS GIS Cut Line= 3
      2036774.64      181840.974     2037129.366      181759.331
     2037484.092      181677.687
#Sta/Elev= 30
       0 1794.99    29.5  1774.8    45.9 1762.31    55.8    1752    62.3 1747.03
    75.4 1742.91    85.3 1737.65     118 1709.83     164 1675.62   186.9    1660
   216.4  1642.2  248.691626.838   268.9 1618.41  293.211612.239   314.8 1609.98
  338.691610.746   347.6 1609.12     356  1604.4   360.7 1602.63   367.3 1602.03
   377.1 1604.67  420.291607.719   468.9 1609.47  505.051612.018   560.8 1613.17
   578.81611.955     610 1614.42   695.2 1617.82  726.63 1617.46     728 1617.56
#Mann= 10 ,-1 , 0
       0     .12       0  248.69     .06       0  293.21    .016       0
  338.69     .12       0     356    .045       0   377.1     .12       0
  420.29     .06       0  505.05     .12       0   578.8     .06       0
  726.63     .12       0
Bank Sta=356,377.1
XS Rating Curve= 0 ,0
Exp/Cntr=0.3,0.1

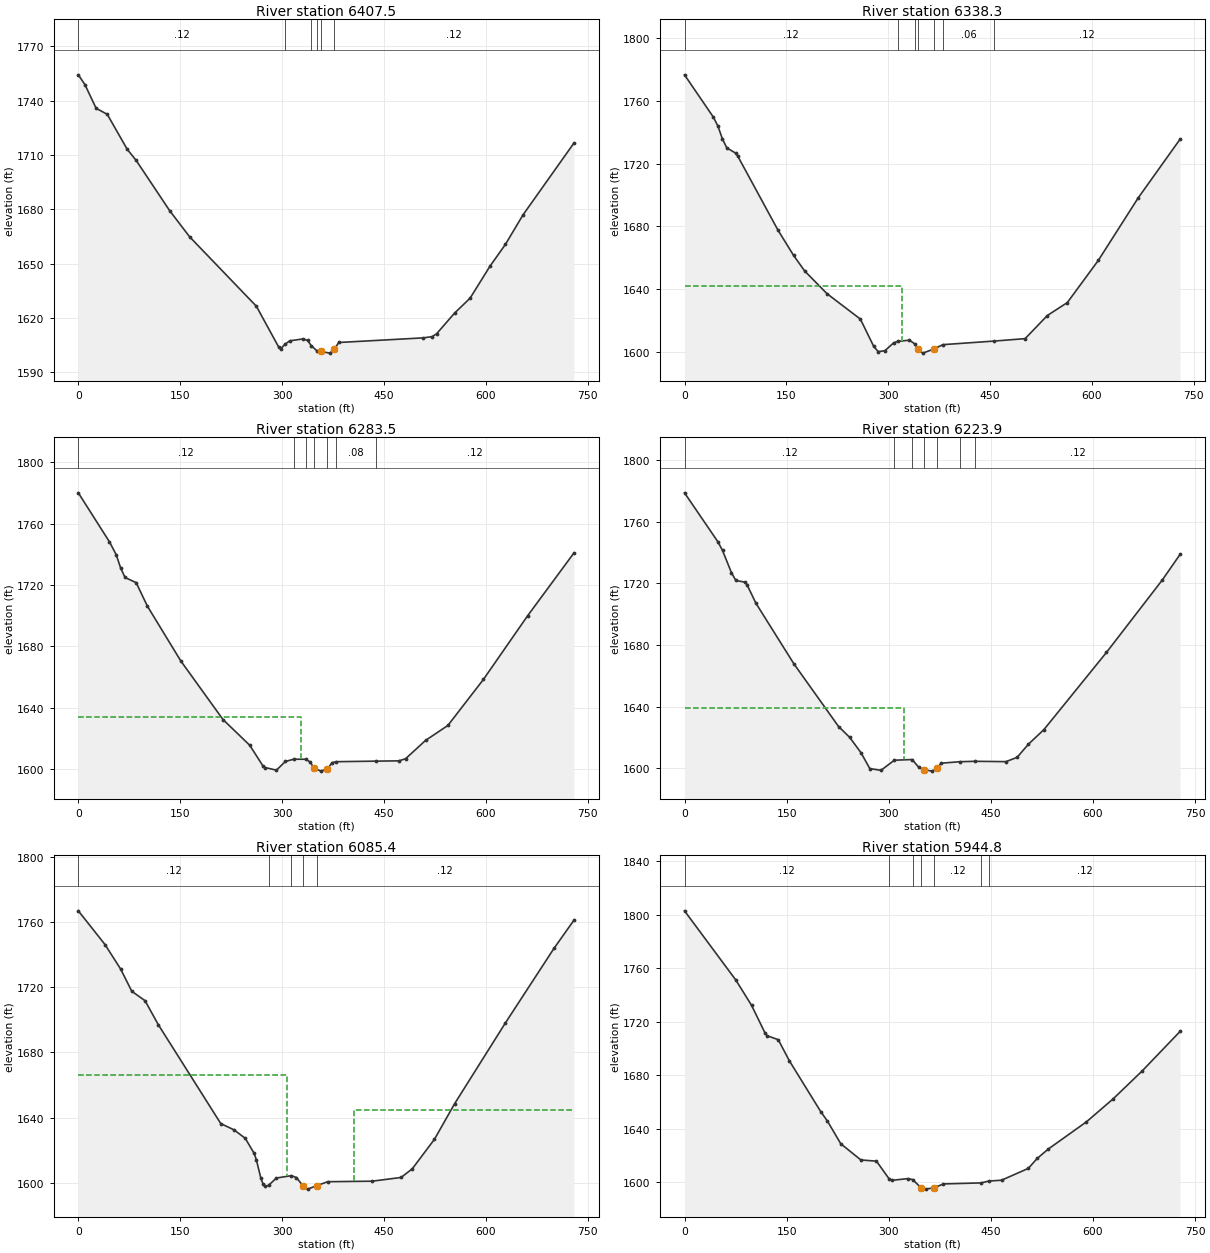
Type RM Length L Ch R = 1 ,6407.5  ,69.2,69.2,69.2
XS GIS Cut Line= 3
     2036806.192      181986.275     2037386.122      181967.807
      2037534.49      181986.656
#Sta/Elev= 30
       0 1754.32     9.8 1748.88    26.2 1735.82    42.6 1732.49    72.1  1713.1
    85.2    1707   134.4 1679.29   163.9 1664.78   262.2 1626.39     295 1603.88
   298.3 1602.95  304.38  1605.4   311.4 1607.28   331.1 1608.34   337.6 1607.49
  342.971604.663  351.481601.691   357.3 1601.39   370.4 1600.47     377  1602.6
   383.5 1606.35   508.1 1608.91   521.2 1609.61   527.8 1611.25     554 1622.57
     577 1630.88   606.2 1648.51     629 1660.61     655 1676.98   729.8 1716.57
#Mann= 6 ,-1 , 0
       0     .12       0  304.38    .016       0  342.97     .06       0
  351.48     .12       0   357.3    .045       0     377     .12       0
Bank Sta=357.3,377
XS Rating Curve= 0 ,0
Exp/Cntr=0.3,0.1

Type RM Length L Ch R = 1 ,6338.3  ,54.8,54.8,54.8
XS GIS Cut Line= 3
     2036810.098      182055.285     2037390.028      182036.818
     2037538.396      182055.666
#Sta/Elev= 30
       0 1776.69    42.6 1749.63    49.2 1743.98    55.7 1735.93    62.3 1730.07
    75.4 1726.72    78.7 1724.59   137.7 1677.56   160.6  1661.5     177 1651.54
   209.8 1637.09     259 1620.85   278.6 1603.48   285.2  1600.1     295 1600.67
   308.1 1605.76  313.781606.606   331.1 1607.42  339.061605.087   344.2 1601.59
   350.8 1599.15   367.2 1601.77   380.5 1604.56  456.151606.848   501.6  1608.4
   534.3 1623.14   563.8 1631.43   609.5 1658.39     668 1698.12   729.8 1735.65
#Mann= 7 ,-1 , 0
       0     .12       0  313.78    .016       0  339.06     .12       0
   344.2    .045       0   367.2     .12       0   380.5     .06       0
  456.15     .12       0
#XS Ineff= 2 , 0
          320.63 1641.67
Permanent Ineff=
       F       F
Bank Sta=344.2,367.2
XS Rating Curve= 0 ,0
Exp/Cntr=0.3,0.1

Type RM Length L Ch R = 1 ,6283.5  ,58.5,59.6,60.7
XS GIS Cut Line= 3
     2036814.005      182109.973     2037393.934      182091.505
     2037542.302      182110.354
#Sta/Elev= 30
       0 1780.11    45.9 1748.11    55.7 1739.87    62.3 1731.17    68.8  1724.9
    85.2 1721.55   101.6 1706.31   150.8 1670.56   213.1 1632.26   252.4 1615.53
   272.1 1601.88   275.4 1600.95   291.8 1599.27   304.9 1604.94  317.311606.426
  335.151606.388   340.9 1604.73   347.5 1600.54   357.3 1598.64   366.9 1600.17
   373.7 1604.14  379.81 1604.79  437.831605.152     472 1605.34   481.9 1606.72
   511.4 1618.68   544.2 1628.41   596.5  1658.4   661.5 1699.85   729.8 1740.88
#Mann= 7 ,-1 , 0
       0     .12       0  317.31    .016       0  335.15     .12       0
   347.5    .045       0   366.9     .12       0  379.81     .08       0
  437.83     .12       0
#XS Ineff= 2 , 0
          328.32 1633.93
Permanent Ineff=
       F       F
Bank Sta=347.5,366.9
XS Rating Curve= 0 ,0
Exp/Cntr=0.3,0.1

Type RM Length L Ch R = 1 ,6223.9  ,139.6,138.5,137.4
XS GIS Cut Line= 2
     2036813.814      182151.688     2037541.702       182164.44
#Sta/Elev= 30
       0 1778.65    49.2 1746.78    55.8 1741.25    68.9  1726.9    75.4 1721.77
    88.5 1720.71    91.8 1719.05   104.9    1707   160.7 1667.69   226.3 1627.02
   242.7 1619.95   259.1 1610.11   272.2 1599.72   288.6 1598.58  308.161605.145
  334.331605.593   344.3 1600.44   351.4 1599.01     364 1598.07   370.6 1599.86
   377.1 1603.22   404.41604.179  426.28 1604.44   472.2 1604.23   488.6 1607.01
     505 1615.45     528 1625.04   619.8 1675.07   701.8 1722.06     728  1738.7
#Mann= 7 ,-1 , 0
       0     .12       0  308.16    .016       0  334.33     .12       0
   351.4    .045       0   370.6     .12       0   404.4     .08       0
  426.28     .12       0
#XS Ineff= 2 , 0
          322.89 1639.29
Permanent Ineff=
       F       F
Bank Sta=351.4,370.6
XS Rating Curve= 0 ,0
Exp/Cntr=0.3,0.1

Type RM Length L Ch R = 1 ,6085.4  ,136.1,140.6,145.2
XS GIS Cut Line= 3
     2036819.213      182306.587     2037399.142       182288.12
     2037547.511      182306.968
#Sta/Elev= 30
       0 1766.73    39.3 1746.08    62.3  1731.1    78.7 1717.49    98.3 1711.68
     118 1696.85   209.8 1636.42   229.5 1632.55   245.9 1627.38     259 1618.14
   262.2 1614.26   268.8 1603.01   272.1 1599.36   275.4 1597.91  280.191598.659
   291.8  1603.1  313.881604.555   321.2 1603.36   331.1  1598.2   337.6 1596.29
   350.8 1598.37   367.2 1600.83   432.7 1601.15   475.3 1603.44   491.7  1608.7
   524.5 1626.85     554 1648.51     629 1698.12   700.5 1743.75   729.8 1760.96
#Mann= 5 ,-1 , 0
       0     .12       0  280.19    .016       0  313.88     .12       0
   331.1    .045       0   350.8     .12       0
#XS Ineff= 2 , 0
          306.61 1666.19  406.11            1645
Permanent Ineff=
       F       F
Bank Sta=331.1,350.8
XS Rating Curve= 0 ,0
Exp/Cntr=0.3,0.1

Type RM Length L Ch R = 1 ,5944.8  ,103,102.6,102.2
XS GIS Cut Line= 3
     2036782.254      182373.888     2037141.028      182435.345
     2037499.803      182496.802
#Sta/Elev= 30
       0 1802.79    75.4 1751.08    98.4 1732.29     118 1711.87   121.3 1709.54
   137.7 1706.56   154.1 1690.73     200 1652.92   209.9 1645.79   229.6  1628.8
   259.1 1616.73     282 1615.84  300.851602.405     305 1601.54   327.9  1602.8
  335.121602.099   347.6  1595.9   354.2 1594.95   367.2 1596.08   380.4 1598.84
  435.491599.592  446.981600.969   465.7 1601.61     505 1610.42   518.1 1617.89
   534.5 1624.94   590.3 1645.15   629.6 1662.34   672.2 1683.16     728 1712.74
#Mann= 7 ,-1 , 0
       0     .12       0  300.85    .016       0  335.12     .12       0
   347.6    .045       0   367.2     .12       0  435.49     .06       0
  446.98     .12       0
Bank Sta=347.6,367.2
XS Rating Curve= 0 ,0
Exp/Cntr=0.3,0.1

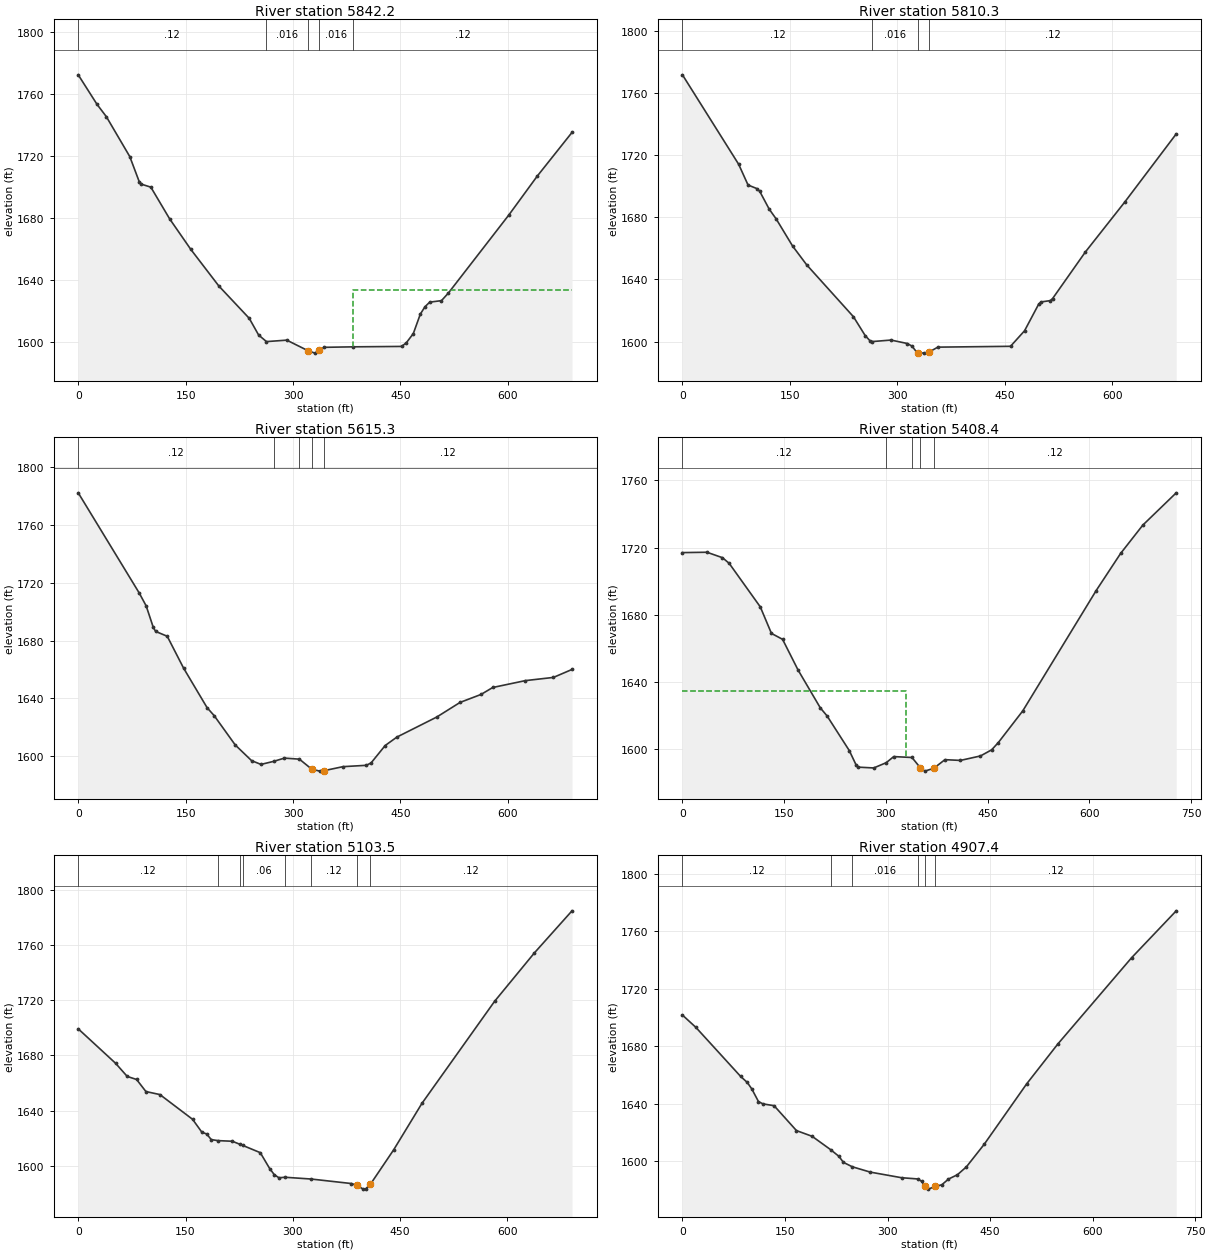
Type RM Length L Ch R = 1 ,5842.2  ,31.9,31.9,31.9
XS GIS Cut Line= 3
     2036794.872      182486.368     2037299.481      182563.188
     2037476.503      182590.306
#Sta/Elev= 30
       0  1772.3    26.2  1753.3    39.3 1745.32      72 1719.61    85.1 1703.53
    88.3 1701.83   101.4 1699.91   127.6 1679.52     157 1659.94   196.3 1636.25
   238.8 1615.39   251.9 1604.64  262.831600.395   291.2 1601.34   320.6  1594.6
   330.5 1592.97   336.8 1594.99   343.6 1596.71  383.821597.025   451.5 1597.29
   458.1 1599.62   467.9 1605.57   477.7 1618.13   484.2 1622.87   490.8 1625.83
   507.2 1626.79   516.9  1631.7   601.6 1682.17   640.7 1706.88   689.5  1735.2
#Mann= 5 ,-1 , 0
       0     .12       0  262.83    .016       0   320.6    .045       0
   336.8    .016       0  383.82     .12       0
#XS Ineff= 2 , 0
                          384.23         1633.93
Permanent Ineff=
       F       F
Bank Sta=320.6,336.8
XS Rating Curve= 0 ,0
Exp/Cntr=0.3,0.1

Type RM Length L Ch R = 1 ,5810.3  ,191.1,194.9,198.4
XS GIS Cut Line= 3
     2036782.719       182516.75     2037287.328       182593.57
     2037464.351      182620.688
#Sta/Elev= 30
       0  1771.6    78.5 1714.05    91.6 1700.71   104.7 1698.27     108 1696.56
   121.1 1685.23   130.9 1678.88   153.8 1661.46   173.4  1649.4   238.8 1615.96
   255.2 1603.83   261.8 1600.56   265.21599.997   291.2 1600.97   314.1 1598.74
   320.6 1597.05   327.2 1593.11   329.4 1592.81     337 1592.56   344.4 1593.26
   356.6 1596.41   458.1 1596.95   477.7 1606.94   497.3 1623.96   500.6 1625.48
   513.7 1626.35   516.9  1627.7   562.5 1657.55   617.9 1689.92   689.5 1733.59
#Mann= 4 ,-1 , 0
       0     .12       0   265.2    .016       0   329.4    .045       0
   344.4     .12       0
Bank Sta=329.4,344.4
XS Rating Curve= 0 ,0
Exp/Cntr=0.3,0.1

Type RM Length L Ch R = 1 ,5615.3  ,207.7,206.9,206.1
XS GIS Cut Line= 3
      2036729.59      182647.406     2037215.846      182802.607
     2037386.403      182857.219
#Sta/Elev= 30
       0 1782.44    85.1 1713.05    94.9 1704.03   104.7  1689.3     108 1686.39
   124.3 1682.99   147.2 1660.83     180 1633.45   189.8    1628   219.2 1607.67
   242.1 1596.76   255.2 1594.17  272.821596.271   287.9 1598.54  308.841597.809
   325.8 1590.98     337 1589.51   343.6 1589.86   369.7 1592.61   402.4 1593.54
     409 1595.24   428.6 1607.26     445 1613.12   500.6    1627   533.2 1637.15
   562.5 1642.68   578.8 1647.49   624.4 1652.26   663.5 1654.47   689.5    1660
#Mann= 5 ,-1 , 0
       0     .12       0  272.82    .016       0  308.84     .12       0
   325.8    .045       0   343.6     .12       0
Bank Sta=325.8,343.6
XS Rating Curve= 0 ,0
Exp/Cntr=0.3,0.1

Type RM Length L Ch R = 1 ,5408.4  ,301.2,304.9,308
XS GIS Cut Line= 3
     2036636.648      182848.531      2036987.14      182946.774
     2037337.631      183045.018
#Sta/Elev= 30
       0 1717.02    36.1 1717.23      59 1713.99    68.9 1710.62   114.8 1684.69
   131.2 1668.92   147.6  1665.4   170.5  1647.1   203.3 1624.57   213.2 1619.82
     246 1599.16   255.8 1590.81   259.1 1589.31     282 1588.83  300.441591.963
   311.5 1595.59  338.391595.059   350.9 1588.85   357.4 1586.94   370.6 1588.65
     387 1593.76   409.9 1593.32   439.4 1595.98   455.8  1599.6   465.7 1603.94
   501.7 1622.78     610 1694.44     646 1716.52   678.8 1733.41     728  1752.6
#Mann= 5 ,-1 , 0
       0     .12       0  300.44    .016       0  338.39     .12       0
   350.9    .045       0   370.6     .12       0
#XS Ineff= 2 , 0
          329.23 1634.43
Permanent Ineff=
       F       F
Bank Sta=350.9,370.6
XS Rating Curve= 0 ,0
Exp/Cntr=0.3,0.1

Type RM Length L Ch R = 1 ,5103.5  ,196.5,196.1,194.6
XS GIS Cut Line= 3
     2036579.271      183110.611     2036895.236      183215.203
     2037221.661      183360.978
#Sta/Elev= 30
       0  1699.3    52.2 1674.31    68.5 1664.74    81.6 1662.53    94.6 1653.78
   114.2 1651.57   159.9  1633.6   172.9 1624.21   179.5 1622.99     186 1618.88
  195.571618.135   215.4 1617.69  226.681615.339  229.881614.692   254.5  1609.4
   267.6  1597.9   274.1 1593.41   280.6 1591.17  288.911591.552  325.721590.254
     382 1586.98   389.6 1585.66   398.4 1582.93   401.7 1583.06   408.3 1586.33
   441.1 1611.57   480.4 1645.11   582.1  1719.3   637.8 1754.48   690.3 1784.97
#Mann= 8 ,-1 , 0
       0     .12       0  195.57    .016       0  226.68     .12       0
  229.88     .06       0  288.91    .016       0  325.72     .12       0
   389.6    .045       0   408.3     .12       0
Bank Sta=389.6,408.3
XS Rating Curve= 0 ,0
Exp/Cntr=0.3,0.1

Type RM Length L Ch R = 1 ,4907.4  ,255,249,243.1
XS GIS Cut Line= 3
     2036504.481      183265.919     2036923.882      183432.651
     2037188.205      183492.547
#Sta/Elev= 30
       0  1701.6    19.6 1693.07      85 1659.01    94.8 1654.76   101.4 1650.29
   111.2 1641.48   117.7 1639.86   134.1 1638.58   166.8 1621.28   189.7 1617.31
  216.981607.955   228.9 1603.38   235.5 1599.19  248.481596.121   274.7 1592.42
   320.5 1588.52  344.311587.644   349.9 1586.04   354.5 1582.59   359.8 1580.58
   369.5 1582.46   379.4 1583.58   389.2 1587.57   402.3 1590.59   415.4 1596.05
   441.5 1611.78   503.6 1653.78   549.3 1681.56     657 1741.41   722.4 1774.08
#Mann= 6 ,-1 , 0
       0     .12       0  216.98     .06       0  248.48    .016       0
  344.31     .12       0   354.5    .045       0   369.5     .12       0
Bank Sta=354.5,369.5
XS Rating Curve= 0 ,0
Exp/Cntr=0.3,0.1

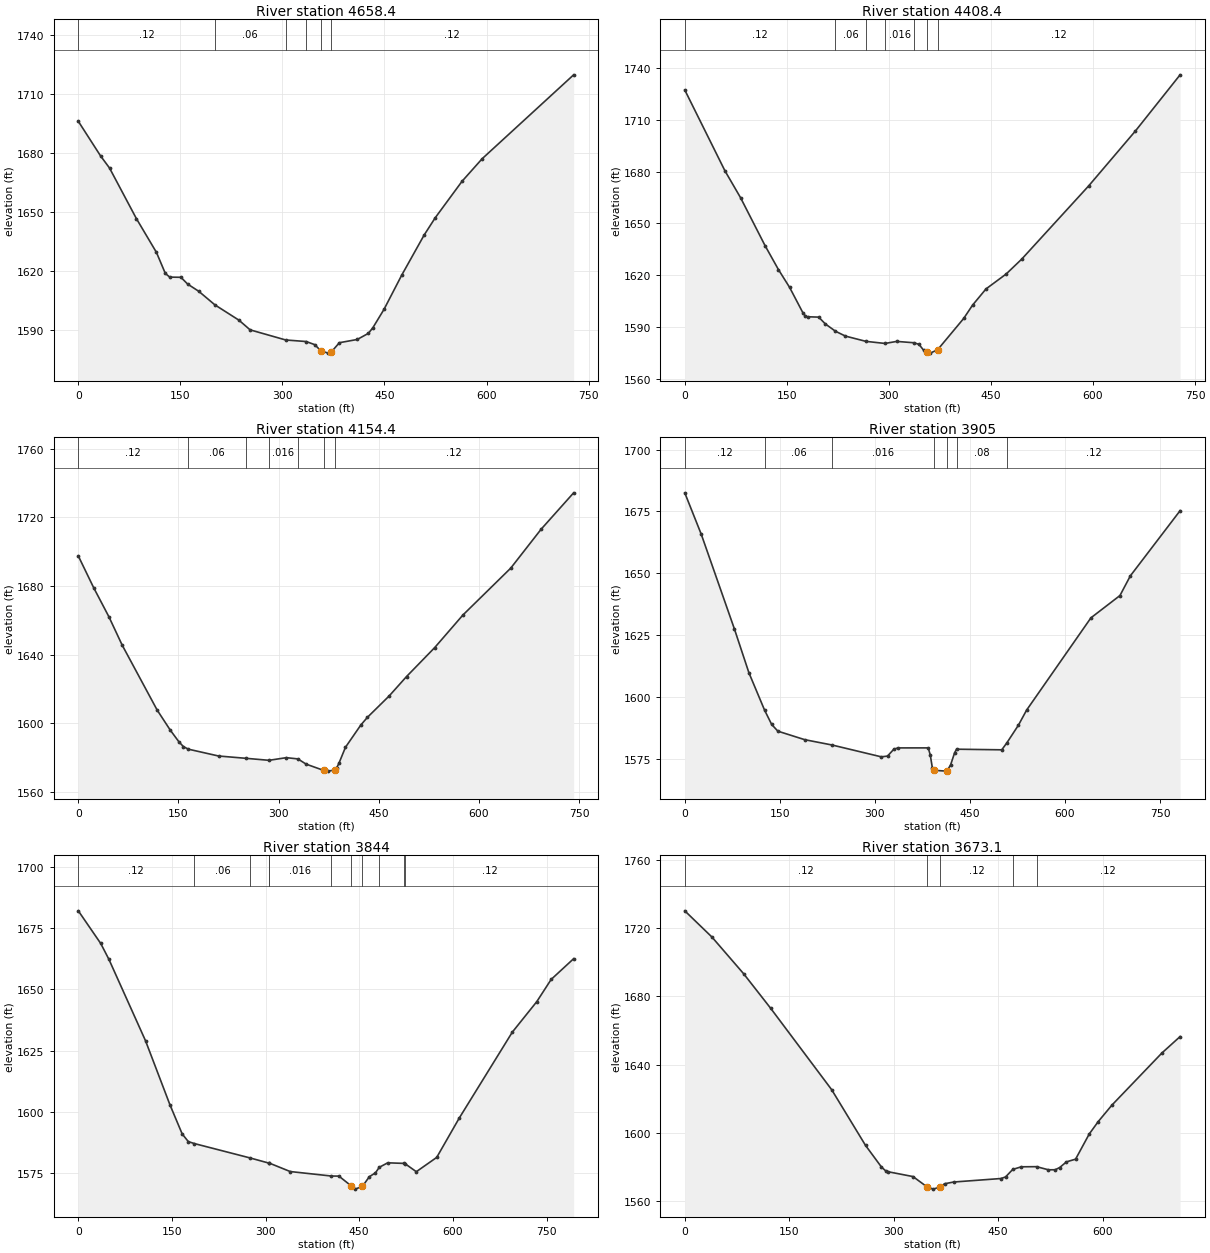
Type RM Length L Ch R = 1 ,4658.4  ,252.1,250,247.9
XS GIS Cut Line= 3
     2036432.489      183602.736     2036794.147      183643.961
     2037155.805      183685.187
#Sta/Elev= 30
       0 1696.15    32.8 1678.47    45.9 1672.33    85.3 1646.61   114.8 1629.38
   127.9 1618.63   134.4 1616.75   150.8 1616.66   160.7 1613.21   177.1 1609.51
  200.691602.628   236.1 1594.81   252.5 1589.88  304.851584.719  334.861583.932
   347.6 1582.33   356.5 1579.18   367.3 1578.02   371.5 1578.48   383.7 1583.33
   409.9 1584.97   426.3 1588.09   432.9 1590.95   449.3 1600.32   475.5 1617.86
   508.3  1638.2   524.7 1647.05     564 1665.58   593.6 1677.09     728 1719.83
#Mann= 6 ,-1 , 0
       0     .12       0  200.69     .06       0  304.85    .016       0
  334.86     .12       0   356.5    .045       0   371.5     .12       0
Bank Sta=356.5,371.5
XS Rating Curve= 0 ,0
Exp/Cntr=0.3,0.1

Type RM Length L Ch R = 1 ,4408.4  ,253.2,254,254
XS GIS Cut Line= 3
     2036410.819       183885.37      2036774.74      183892.952
     2037138.661      183900.534
#Sta/Elev= 30
       0 1727.23      59 1680.48      82 1664.89     118 1637.17   137.7  1623.3
   154.1    1613   173.8 1598.19   177.1  1596.5   180.4 1596.02   196.8 1595.82
   206.6 1591.88  221.481587.651   236.1 1584.85  266.191581.802   294.3 1580.59
   311.5 1581.77  337.221580.978   344.3 1580.03   350.9 1576.75   356.5 1575.67
   360.7 1574.99   371.5  1576.9   409.9 1595.03     423 1602.77   442.7 1612.12
   472.2 1620.71   495.2 1629.36   593.6 1671.72   662.4 1703.53     728 1735.98
#Mann= 7 ,-1 , 0
       0     .12       0  221.48     .06       0  266.19     .12       0
   294.3    .016       0  337.22     .12       0   356.5    .045       0
   371.5     .12       0
Bank Sta=356.5,371.5
XS Rating Curve= 0 ,0
Exp/Cntr=0.3,0.1

Type RM Length L Ch R = 1 ,4154.4  ,217,249.5,280.5
XS GIS Cut Line= 3
     2036412.963      184134.931     2036858.778      184146.193
     2037139.145      184052.275
#Sta/Elev= 30
       0 1697.48      23    1679    45.9 1662.02    65.6 1645.64     118 1607.81
   137.7 1596.09   150.8 1589.21   157.4 1586.49  164.791585.008   209.9 1581.04
  250.661579.701  285.521578.525   311.5 1580.07  328.791579.336     341 1576.32
   367.3 1572.66   373.8 1572.23   383.7 1572.85   386.9 1574.24   390.2 1576.78
     400 1586.12     423 1599.08   432.8 1603.52   465.4 1615.98   491.4 1627.27
   533.7 1644.18   575.9 1663.13   647.4 1690.38   692.9 1713.03   741.6 1734.23
#Mann= 7 ,-1 , 0
       0     .12       0  164.79     .06       0  250.66     .12       0
  285.52    .016       0  328.79     .12       0   367.3    .045       0
   383.7     .12       0
Bank Sta=367.3,383.7
XS Rating Curve= 0 ,0
Exp/Cntr=0.3,0.1

Type RM Length L Ch R = 1 ,3905    ,54.5,61,62.5
XS GIS Cut Line= 4
     2036396.332      184204.661     2036715.549      184310.255
     2036742.892      184435.255     2036999.687       184621.84
#Sta/Elev= 30
       0 1682.52    26.1  1665.7    78.3 1627.48   101.2 1609.75  125.941594.618
   137.1 1588.85   146.9 1586.12   189.3 1582.68  232.631580.513   310.1 1575.74
   319.9 1576.04   329.7 1578.77   336.2 1579.35   384.2 1579.36   387.4 1576.46
   390.6  1571.4   393.8 1570.28     413 1569.96   413.9 1570.15   419.4 1572.43
   425.8 1577.38  428.871578.829   500.2 1578.58  508.06 1581.33   526.4 1588.51
   539.4 1594.64   640.9 1631.96   686.7 1640.98   703.1 1648.94   781.6  1675.3
#Mann= 7 ,-1 , 0
       0     .12       0  125.94     .06       0  232.63    .016       0
   393.8    .045       0   413.9    .016       0  428.87     .08       0
  508.06     .12       0
Bank Sta=393.8,413.9
XS Rating Curve= 0 ,0
Exp/Cntr=0.3,0.1

Type RM Length L Ch R = 1 ,3844    ,201,170.9,145.7
XS GIS Cut Line= 4
     2036352.061      184222.891      2036672.58      184312.859
     2036698.622      184453.484     2036955.416      184640.069
#Sta/Elev= 30
       0 1682.07    35.9 1668.75      49 1662.28   107.7 1629.02   146.9 1602.82
   166.4    1591   176.2 1587.88  185.981587.071  275.381581.192  305.041579.117
  306.061579.096   339.4 1575.66  405.321573.829   417.4  1573.8   436.9 1569.85
   443.4 1568.48   455.1 1569.61   466.2 1573.56   475.9 1575.11  482.091577.387
   495.6 1579.22  521.311578.988  523.731578.798   541.4 1575.59   574.1 1581.43
   610.1 1597.45   695.2 1632.56   734.4 1645.01   757.4 1654.07   793.4 1662.53
#Mann= 11 ,-1 , 0
       0     .12       0  185.98     .06       0  275.38    .016       0
  305.04     .12       0  306.06    .016       0  405.32     .12       0
   436.9    .045       0   455.1     .12       0  482.09    .016       0
  521.31     .08       0  523.73     .12       0
Bank Sta=436.9,455.1
XS Rating Curve= 0 ,0
Exp/Cntr=0.3,0.1

Type RM Length L Ch R = 1 ,3673.1  ,319.2,309.1,298.4
XS GIS Cut Line= 4
     2036246.799      184577.182     2036529.351      184535.516
     2036765.824      184633.862     2036934.299      184654.005
#Sta/Elev= 30
       0 1730.24      39 1714.86    84.4 1693.39   123.3 1673.07     211 1625.24
   259.6 1592.56   282.4  1579.9   288.8 1577.52   292.1 1577.09   327.8 1574.26
   347.9 1568.22   356.9 1566.89   366.6 1568.18   373.1 1570.03   386.1 1571.06
   454.2 1573.12   460.7 1574.04  471.031578.456   483.4    1580  505.171580.073
   522.3 1578.24     532 1578.26   538.5 1579.58   548.2  1582.9   561.3 1584.48
   580.9 1599.25   593.9 1606.58   613.5 1616.21   685.3  1646.8   711.4 1656.43
#Mann= 5 ,-1 , 0
       0     .12       0   347.9    .045       0   366.6     .12       0
  471.03    .016       0  505.17     .12       0
Bank Sta=347.9,366.6
XS Rating Curve= 0 ,0
Exp/Cntr=0.3,0.1