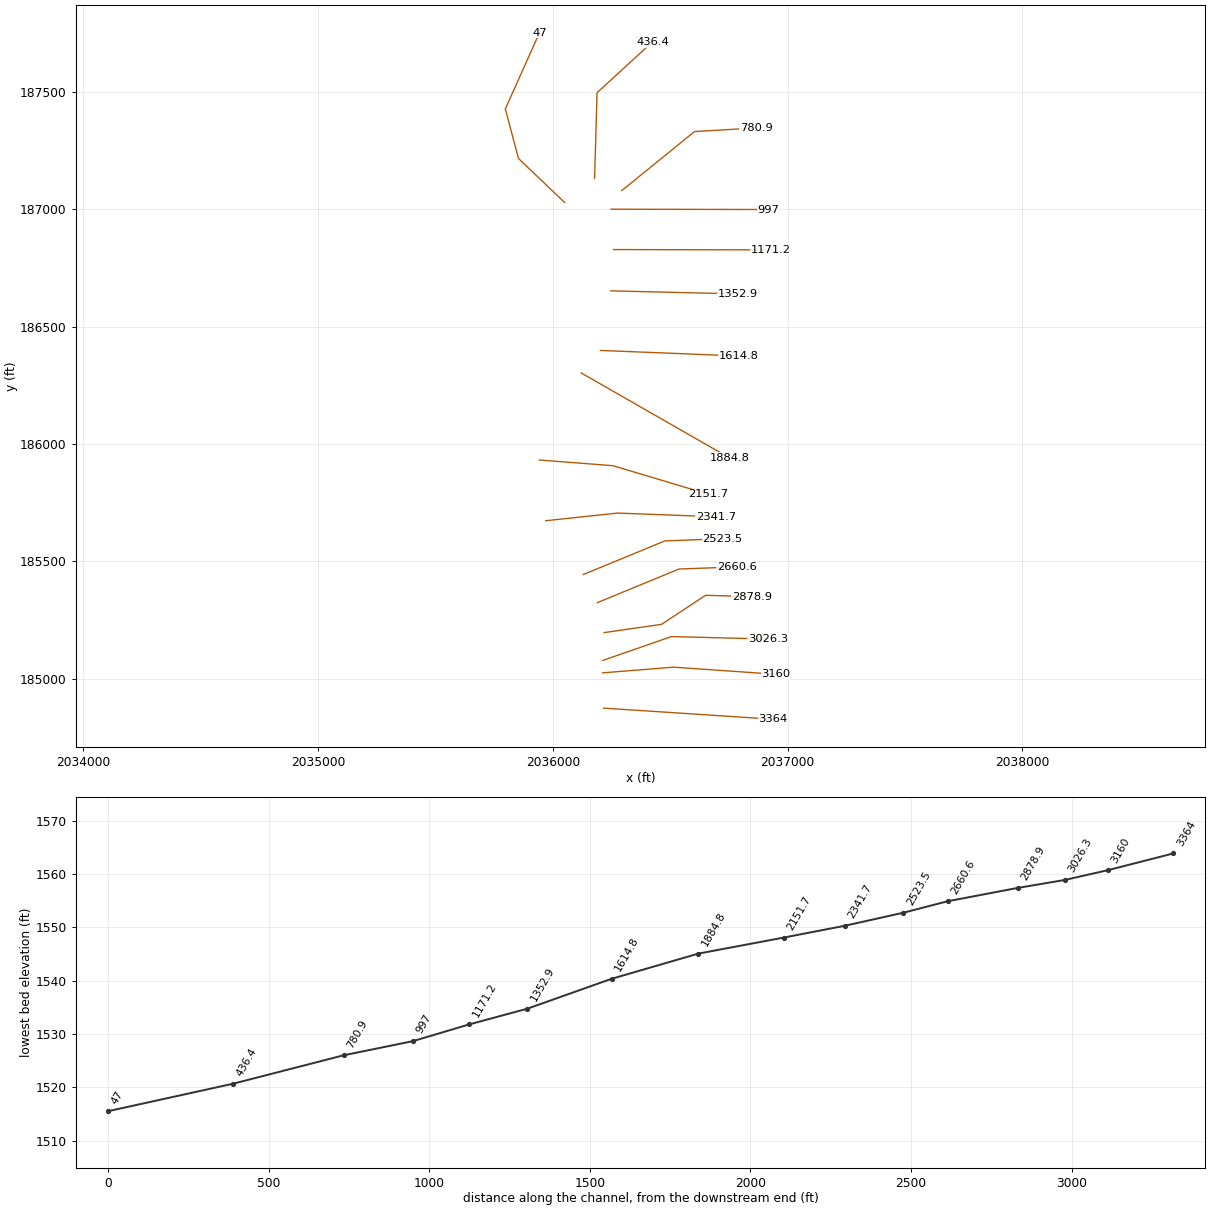
HEC-RAS study FITZRN.prj: FITZRN

--- FITZRN.g01 (geometry) --- (continued)

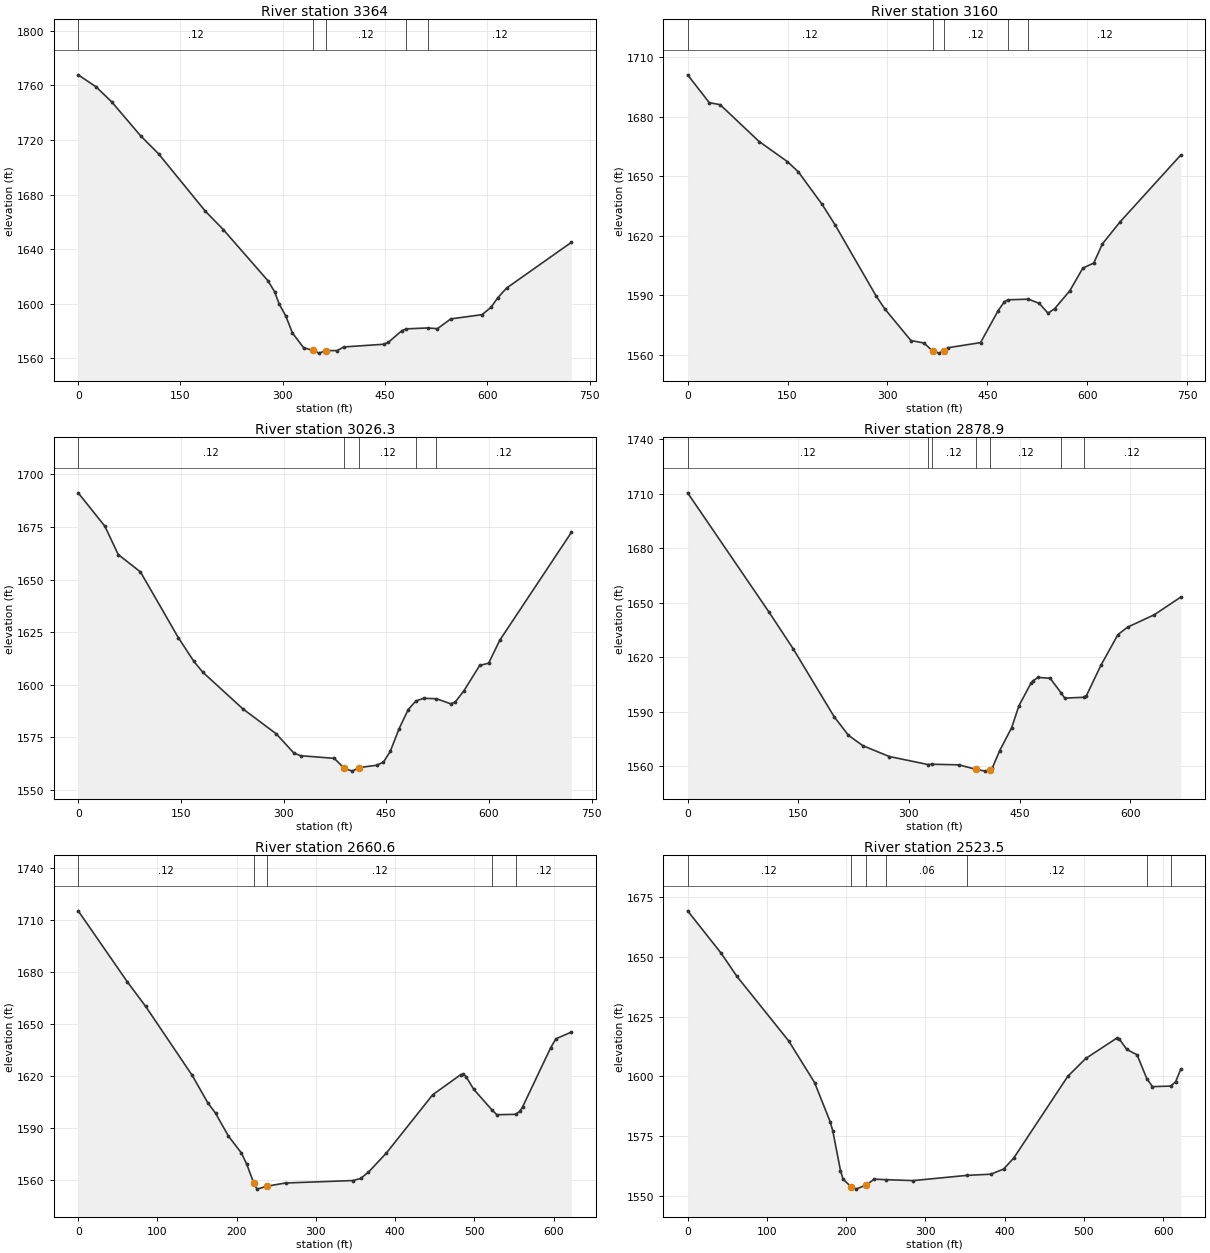
Type RM Length L Ch R = 1 ,3364    ,203.2,204,203.3
XS GIS Cut Line= 2
     2036215.549      184875.359     2036937.104      184828.184
#Sta/Elev= 30
       0 1767.63    26.2 1758.83    49.1 1747.86    91.6 1722.94   117.8 1709.83
   186.5 1667.75   212.7 1654.36   278.1 1616.94   287.9 1608.92   294.5 1600.07
   304.3 1591.14   314.1 1578.71   330.5 1567.78     344 1565.93   353.4 1563.86
   363.2 1565.77   379.5 1565.69   389.4 1568.37   448.2 1570.37   454.8 1571.78
   474.4 1580.22  481.181581.629  512.341582.295   526.8 1581.77   546.4 1588.94
   592.2 1592.03   605.3  1597.4   615.1 1604.32   628.2 1611.52   723.1 1644.94
#Mann= 5 ,-1 , 0
       0     .12       0     344    .045       0   363.2     .12       0
  481.18    .016       0  512.34     .12       0
Bank Sta=344,363.2
XS Rating Curve= 0 ,0
Exp/Cntr=0.3,0.1

Type RM Length L Ch R = 1 ,3160    ,132.7,133.7,134.6
XS GIS Cut Line= 3
     2036212.212      185025.622     2036513.726      185049.839
     2036950.405      185019.563
#Sta/Elev= 30
       0 1701.25    32.5 1687.19    48.8 1686.18   107.3 1667.58   149.6 1657.47
   165.9 1652.37   201.7 1635.92   221.2 1625.58     283 1589.55     296 1583.03
   335.2 1567.08   354.8 1565.84   368.2 1561.67   377.6 1560.72   384.2 1561.94
   390.7 1563.44   439.7 1566.03   465.8 1582.02   475.6 1586.73  480.931587.639
  511.461587.977   527.9 1585.81     541 1580.89   550.8 1583.12   573.6 1592.18
   593.2 1603.62   609.6 1606.22   622.6 1615.89   648.8 1626.88   740.2 1660.74
#Mann= 5 ,-1 , 0
       0     .12       0   368.2    .045       0   384.2     .12       0
  480.93    .016       0  511.46     .12       0
Bank Sta=368.2,384.2
XS Rating Curve= 0 ,0
Exp/Cntr=0.3,0.1

Type RM Length L Ch R = 1 ,3026.3  ,133.5,147.3,161
XS GIS Cut Line= 3
     2036212.945      185078.484     2036504.611      185180.047
      2036916.07       185169.63
#Sta/Elev= 30
       0 1691.28      39 1675.37    58.5 1661.92      91 1653.64   146.3 1622.37
     169  1611.1   182.1 1605.92   240.6  1588.5   289.3 1576.63   315.4  1567.4
   325.2 1566.22   374.2 1564.97   388.3 1560.33   400.3 1558.89   410.1 1560.56
   436.2  1561.7     446 1563.22   455.8 1568.23   468.9 1579.16     482 1588.11
  493.251592.259   504.8 1593.54  523.411593.324     544 1590.94   550.6 1591.67
   563.6 1597.16   586.5 1609.16   599.6 1610.24   615.9 1621.18   720.4 1672.43
#Mann= 5 ,-1 , 0
       0     .12       0   388.3    .045       0   410.1     .12       0
  493.25    .016       0  523.41     .12       0
Bank Sta=388.3,410.1
XS Rating Curve= 0 ,0
Exp/Cntr=0.3,0.1

Type RM Length L Ch R = 1 ,2878.9  ,221.9,218.3,214.6
XS GIS Cut Line= 4
     2036218.153      185196.974     2036462.945       185232.13
     2036650.445      185355.828     2036847.059       185350.62
#Sta/Elev= 30
       0 1710.52   110.6 1644.74   143.2 1624.66   198.5 1587.43     218 1577.13
   237.5 1571.41   273.4 1565.43  325.891561.022  331.261561.183   367.8 1560.85
   390.5 1558.42   403.6 1557.39   410.6 1558.28   413.3 1559.33   423.1 1568.65
   439.4 1581.37   449.1 1593.29   465.4 1605.69   468.7  1607.2   475.2 1608.96
   491.6 1608.46  506.861600.147   511.3 1597.57  537.021598.008   540.8    1599
   560.4 1615.69   583.4 1632.51   596.5 1636.61   632.6 1643.41   668.6 1653.14
#Mann= 7 ,-1 , 0
       0     .12       0  325.89     .06       0  331.26     .12       0
   390.5    .045       0   410.6     .12       0  506.86    .016       0
  537.02     .12       0
Bank Sta=390.5,410.6
XS Rating Curve= 0 ,0
Exp/Cntr=0.3,0.1

Type RM Length L Ch R = 1 ,2660.6  ,136.7,137.1,136.8
XS GIS Cut Line= 3
     2036189.507      185324.578     2036537.163      185467.807
     2036783.257      185476.922
#Sta/Elev= 30
       0 1715.37    62.1 1674.36      85 1660.35   143.9 1620.44   163.5 1604.72
   173.3 1598.67   189.6 1585.47     206 1575.71   212.5 1569.45  221.32  1558.7
   225.6 1554.89   238.7 1556.63   261.6 1558.42   346.6 1559.84   356.4 1561.02
   366.2 1564.65     389 1575.76   447.3 1609.29   482.9 1620.96   486.2 1621.06
   489.4 1619.83   499.1 1612.48  521.941600.643   528.3 1597.79  552.071598.037
   557.5 1599.82   560.7 1602.22   596.3 1636.48   602.8 1641.57   622.3 1645.44
#Mann= 5 ,-1 , 0
       0     .12       0  221.32    .045       0   238.7     .12       0
  521.94    .016       0  552.07     .12       0
Bank Sta=221.32,238.7
XS Rating Curve= 0 ,0
Exp/Cntr=0.3,0.1

Type RM Length L Ch R = 1 ,2523.5  ,191.4,181.8,172
XS GIS Cut Line= 3
     2036129.611       185444.37     2036477.267      185587.599
     2036723.361      185596.714
#Sta/Elev= 30
       0 1669.38    42.5 1651.53    62.1 1641.96   127.5 1614.88   160.2 1597.42
   179.8 1581.06   183.1  1577.3   192.9 1560.53   196.2 1556.94     206  1553.8
   212.5 1552.75   225.6 1554.53   235.4 1556.92  250.111556.719   284.5 1556.32
  352.321558.514   382.5    1559   398.7 1561.15   411.6  1565.8   479.7 1600.01
   502.4 1607.51   541.3 1615.98   544.5 1615.78   554.2 1611.29   567.2 1609.03
  579.431599.085   586.6  1595.7  609.561595.936   615.8 1597.72   622.3 1603.01
#Mann= 7 ,-1 , 0
       0     .12       0     206    .045       0   225.6     .12       0
  250.11     .06       0  352.32     .12       0  579.43    .016       0
  609.56     .12       0
Bank Sta=206,225.6
XS Rating Curve= 0 ,0
Exp/Cntr=0.3,0.1

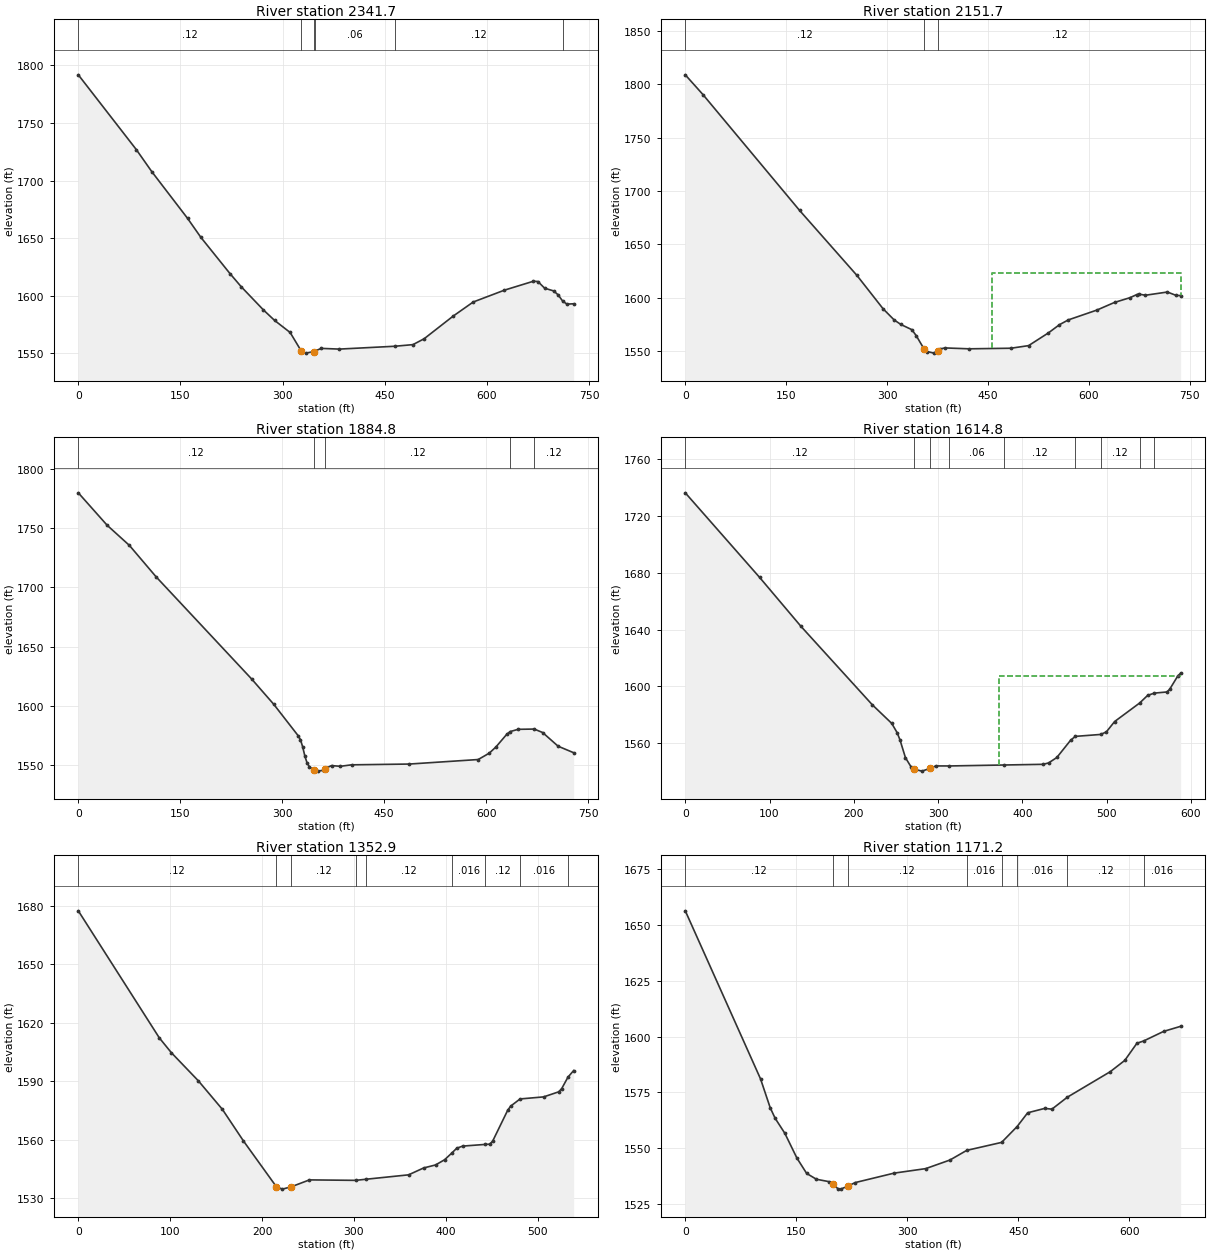
Type RM Length L Ch R = 1 ,2341.7  ,195.7,190,184.2
XS GIS Cut Line= 3
     2035969.455      185673.536     2036275.445      185706.089
     2036694.715      185690.464
#Sta/Elev= 30
       0 1791.77    85.1 1726.95     108 1707.68   160.4 1667.25     180 1650.72
   222.6 1619.39     239 1608.04   271.7 1587.84   288.1 1578.74     311 1568.22
   327.4 1552.09   333.9 1550.31   346.1 1551.68  347.611552.235   356.9 1554.42
   383.1 1553.81  464.791556.278   491.3 1557.68   507.7 1562.76   550.3  1582.4
   579.8 1594.66   625.7 1604.96   668.3  1612.7   674.8 1612.43   684.7 1606.64
   697.8  1604.3   704.3 1600.99  711.181595.446   717.4 1592.84   727.3 1593.12
#Mann= 6 ,-1 , 0
       0     .12       0   327.4    .045       0   346.1     .12       0
  347.61     .06       0  464.79     .12       0  711.18    .016       0
Bank Sta=327.4,346.1
XS Rating Curve= 0 ,0
Exp/Cntr=0.3,0.1

Type RM Length L Ch R = 1 ,2151.7  ,272,266.9,261.6
XS GIS Cut Line= 3
     2035942.932       185932.16     2036255.913      185907.911
     2036660.861      185786.818
#Sta/Elev= 30
       0 1808.94    26.2 1790.48     170 1681.82   255.1 1621.05   294.3 1589.54
   310.6 1579.21   320.5 1574.98   336.9 1570.08   343.4 1564.48   355.3 1551.73
   359.8 1549.58   369.6  1548.1   376.2 1550.47   379.4 1552.08     386 1552.98
     422 1552.14   484.3 1552.69   510.5 1555.14     540 1567.08   556.4 1574.75
   569.5 1579.23   612.1 1588.46   638.3 1595.63   661.2 1600.05   671.1  1602.9
   674.3 1603.44   684.2 1602.35   716.9 1605.37     730 1602.16   736.6 1602.09
#Mann= 3 ,-1 , 0
       0     .12       0   355.3    .045       0   376.2     .12       0
#XS Ineff= 2 , 0
                           456.3         1623.33
Permanent Ineff=
       F       F
Bank Sta=355.3,376.2
XS Rating Curve= 0 ,0
Exp/Cntr=0.3,0.1

Type RM Length L Ch R = 1 ,1884.8  ,259.1,270,280.8
XS GIS Cut Line= 2
     2036121.086      186302.868     2036753.578      185940.559
#Sta/Elev= 30
       0 1779.79    42.5  1752.4    75.2 1735.44   114.4    1709     255 1622.82
   287.6 1601.44   323.6 1574.88   326.9 1571.55   330.1 1565.67   333.4  1557.7
   336.7 1551.85   339.9 1548.96   346.2 1545.81     353 1545.08   359.6  1545.8
   362.8  1547.2   372.6 1549.73   385.7 1549.15     402 1550.39     487 1551.05
   588.4 1554.86   604.7 1560.23   614.5 1565.45   630.8 1576.38  635.711578.477
   647.2 1580.34  670.841580.555   683.2 1577.65     706  1566.1   728.9  1560.6
#Mann= 5 ,-1 , 0
       0     .12       0   346.2    .045       0   362.8     .12       0
  635.71    .016       0  670.84     .12       0
Bank Sta=346.2,362.8
XS Rating Curve= 0 ,0
Exp/Cntr=0.3,0.1

Type RM Length L Ch R = 1 ,1614.8  ,261.1,261.8,261.8
XS GIS Cut Line= 2
     2036202.528      186398.797     2036789.767      186375.359
#Sta/Elev= 30
       0 1736.16    88.2 1676.64   137.1 1642.31     222 1586.96   244.9 1573.97
   251.4 1567.36   254.7 1562.37   261.2 1549.83   267.7 1543.48     271 1541.77
   280.8 1540.36   290.6 1542.34   297.1 1544.02  313.411544.001  377.73 1544.67
   424.5 1545.15     431 1546.12   440.8 1549.95   457.1 1562.05  462.671564.802
  492.841566.172   499.6 1567.99   509.4 1575.26  539.041588.275   548.5 1593.62
  556.42 1595.25   571.4 1596.05   574.6 1597.88   584.4 1607.39   587.7  1609.3
#Mann= 9 ,-1 , 0
       0     .12       0     271    .045       0   290.6     .12       0
  313.41     .06       0  377.73     .12       0  462.67    .016       0
  492.84     .12       0  539.04    .016       0  556.42     .12       0
#XS Ineff= 2 , 0
                          372.07         1607.44
Permanent Ineff=
       F       F
Bank Sta=271,290.6
XS Rating Curve= 0 ,0
Exp/Cntr=0.3,0.1

Type RM Length L Ch R = 1 ,1352.9  ,181.3,181.7,182.5
XS GIS Cut Line= 2
     2036246.799      186652.703     2036785.861      186639.682
#Sta/Elev= 30
       0 1677.52    88.2 1612.34   101.3 1604.75   130.7 1590.31   156.9 1575.64
   179.7 1559.52   215.6    1536   222.2 1534.77     232 1536.01   251.6 1539.51
  301.891539.269  312.851539.822   359.5  1542.1   375.8 1545.61   388.9 1547.18
   398.7 1549.84  406.611553.301   411.8 1555.71   418.3 1556.84  443.011557.709
   447.7 1557.82     451 1559.38   467.3 1575.14   470.6 1577.34  480.88 1581.03
   506.5 1582.08   522.9 1584.68   526.2 1586.36     5331592.213   539.2  1595.6
#Mann= 9 ,-1 , 0
       0     .12       0   215.6    .045       0     232     .12       0
  301.89     .06       0  312.85     .12       0  406.61    .016       0
  443.01     .12       0  480.88    .016       0     533     .12       0
Bank Sta=215.6,232
XS Rating Curve= 0 ,0
Exp/Cntr=0.3,0.1

Type RM Length L Ch R = 1 ,1171.2  ,173.9,174.3,173.8
XS GIS Cut Line= 2
     2036258.517      186828.484     2036927.788      186827.182
#Sta/Elev= 30
       0  1656.2   101.7 1581.06   114.8 1568.13   121.4 1563.48   134.5 1556.77
   150.9 1545.65     164 1538.82   177.2 1536.22   193.6 1535.19   200.1 1533.88
   206.7 1531.86     210 1531.81   219.8  1533.2   229.6 1534.74   282.1 1538.96
   324.8 1540.97   357.6 1544.82  380.241549.127  427.371552.696   448.4  1559.8
   462.6 1565.93   485.6 1567.89   495.4 1567.56  516.221572.906   574.1 1584.28
   593.8 1589.34   610.2 1597.01  619.291598.031   646.3 1602.31   669.3 1604.58
#Mann= 8 ,-1 , 0
       0     .12       0   200.1    .045       0   219.8     .12       0
  380.24    .016       0  427.37     .12       0   448.4    .016       0
  516.22     .12       0  619.29    .016       0
Bank Sta=200.1,219.8
XS Rating Curve= 0 ,0
Exp/Cntr=0.3,0.1

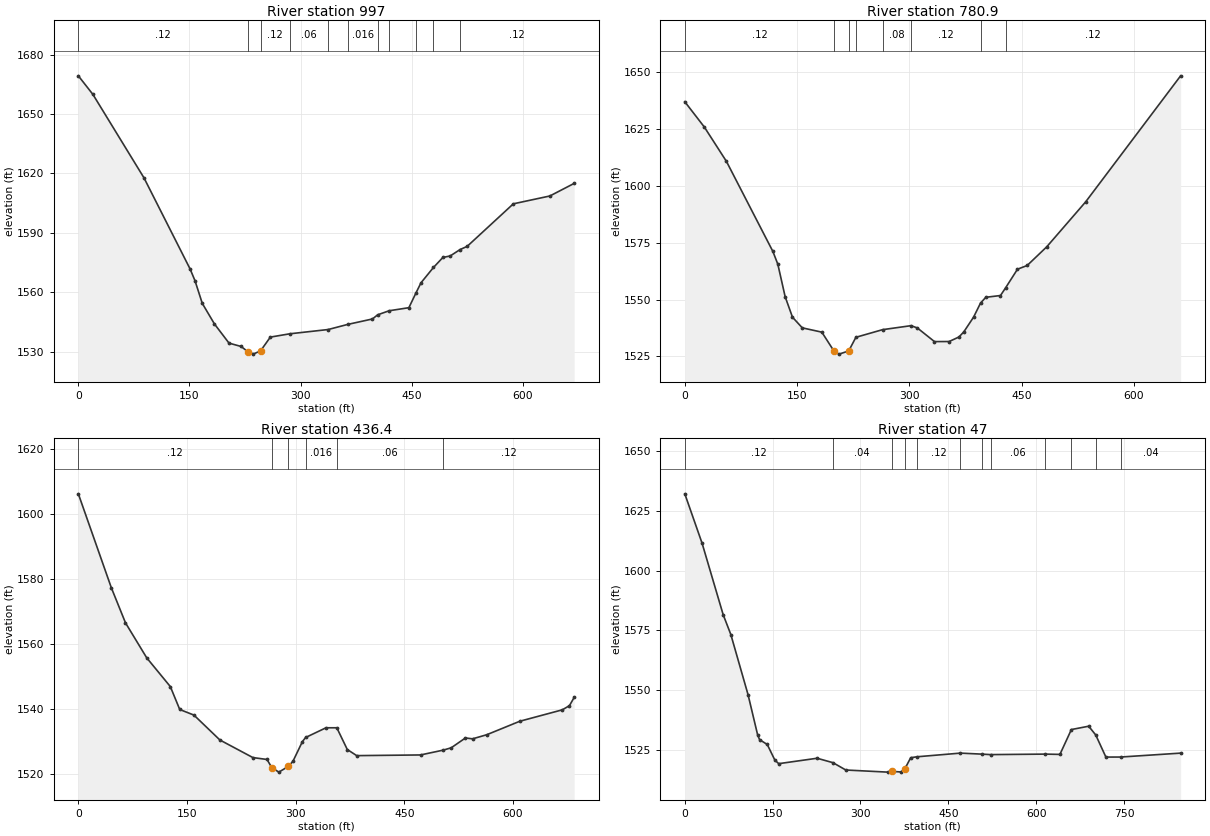
Type RM Length L Ch R = 1 ,997     ,199.9,216.1,231.5
XS GIS Cut Line= 2
     2036248.101      187000.359     2036917.372      186999.057
#Sta/Elev= 30
       0 1669.28    19.7 1659.88    88.6 1617.75   150.9 1571.68   157.5 1565.76
   167.3 1554.34   183.7 1543.95   203.4 1534.25   219.8 1532.55   228.7 1529.95
   236.2 1528.69   246.1  1530.4   259.2 1537.29  285.531538.964  337.291541.122
  363.671543.707     397 1546.45  404.061548.553  419.591550.602   446.2 1552.15
  455.771559.607   462.6 1564.75  479.37 1572.46   492.1 1577.53     502 1578.29
  515.321581.523   524.9 1583.13   587.2 1604.62   636.5 1608.58   669.3 1614.94
#Mann= 11 ,-1 , 0
       0     .12       0   228.7    .045       0   246.1     .12       0
  285.53     .06       0  337.29     .12       0  363.67    .016       0
  404.06     .12       0  419.59    .016       0  455.77     .12       0
  479.37    .016       0  515.32     .12       0
Bank Sta=228.7,246.1
XS Rating Curve= 0 ,0
Exp/Cntr=0.3,0.1

Type RM Length L Ch R = 1 ,780.9   ,324.4,344.5,363.8
XS GIS Cut Line= 3
     2036293.674      187079.786      2036603.57      187331.089
      2036866.59      187346.714
#Sta/Elev= 30
       0 1637.09    26.2 1625.91    55.6 1610.86   117.7  1571.2   124.3  1565.6
   134.1 1551.28   143.9 1542.27     157 1537.59   183.1  1535.7   199.5 1527.28
     206 1526.03     219 1527.42  228.611533.436  264.261536.797  302.291538.551
   310.7 1537.55   333.6 1531.54   353.2 1531.58   366.3 1533.57   372.8 1535.82
   385.9 1542.33  395.151548.505   402.2 1551.04   421.8 1551.82  428.581555.172
   444.5 1563.39   457.5 1565.04   483.6 1573.25   535.6 1593.03   662.5 1648.49
#Mann= 8 ,-1 , 0
       0     .12       0   199.5    .045       0     219     .12       0
  228.61    .016       0  264.26     .08       0  302.29     .12       0
  395.15    .016       0  428.58     .12       0
Bank Sta=199.5,219
XS Rating Curve= 0 ,0
Exp/Cntr=0.3,0.1

Type RM Length L Ch R = 1 ,436.4   ,382.3,389.3,394.5
XS GIS Cut Line= 3
     2036177.788       187131.87     2036188.205      187496.453
     2036423.882      187712.599
#Sta/Elev= 30
       0 1606.23    45.6 1577.34    65.1 1566.58    94.4 1555.83     127 1546.99
     140 1539.95   159.6 1538.23   195.4 1530.58     241 1525.17   260.5 1524.59
     267 1522.11   276.8  1520.7   289.8 1522.44   296.3 1524.04   309.4 1530.11
  313.791531.347   341.9 1534.33  356.841534.331   371.3 1527.65   384.3 1525.77
   472.4 1525.98  503.741527.463   514.8 1528.18   534.4  1531.2   544.2 1530.93
   563.8 1532.19   609.5 1536.34   668.2 1539.85     678 1541.13   684.5 1543.65
#Mann= 6 ,-1 , 0
       0     .12       0     267    .045       0   289.8     .12       0
  313.79    .016       0  356.84     .06       0  503.74     .12       0
Bank Sta=267,289.8
XS Rating Curve= 0 ,0
Exp/Cntr=0.3,0.1

Type RM Length L Ch R = 1 ,47      ,46.7,47,47.3
XS GIS Cut Line= 4
     2036050.184      187029.005      2035853.57      187216.505
      2035797.58      187427.443     2035943.413      187752.964
#Sta/Elev= 30
       0 1632.22    29.5 1611.52    65.5 1581.57    78.6 1573.24     108 1548.02
   124.4 1531.13   127.7 1529.16   140.8 1527.14   153.8 1520.58   160.4  1519.1
   225.9 1521.37  253.021519.509   274.9 1516.44   346.6 1515.55   353.1 1515.88
   369.4 1515.61   375.9    1517   385.7 1521.59  396.121521.975  470.46 1523.52
  506.891523.101  522.081522.895  615.441523.103   640.5 1522.98  660.061533.398
   689.6  1534.8  701.69 1531.12     719 1521.86  744.071521.876   846.6 1523.52
#Mann= 12 ,-1 , 0
       0     .12       0  253.02     .04       0   353.1    .045       0
   375.9     .04       0  396.12     .12       0  470.46     .06       0
  506.89     .12       0  522.08     .06       0  615.44     .12       0
  660.06    .016       0  701.69     .06       0  744.07     .04       0
Bank Sta=353.1,375.9
XS Rating Curve= 0 ,0
Exp/Cntr=0.3,0.1

Chan Stop Cuts=-1
Use User Specified Reach Order=0
Composite Channel Slope=5